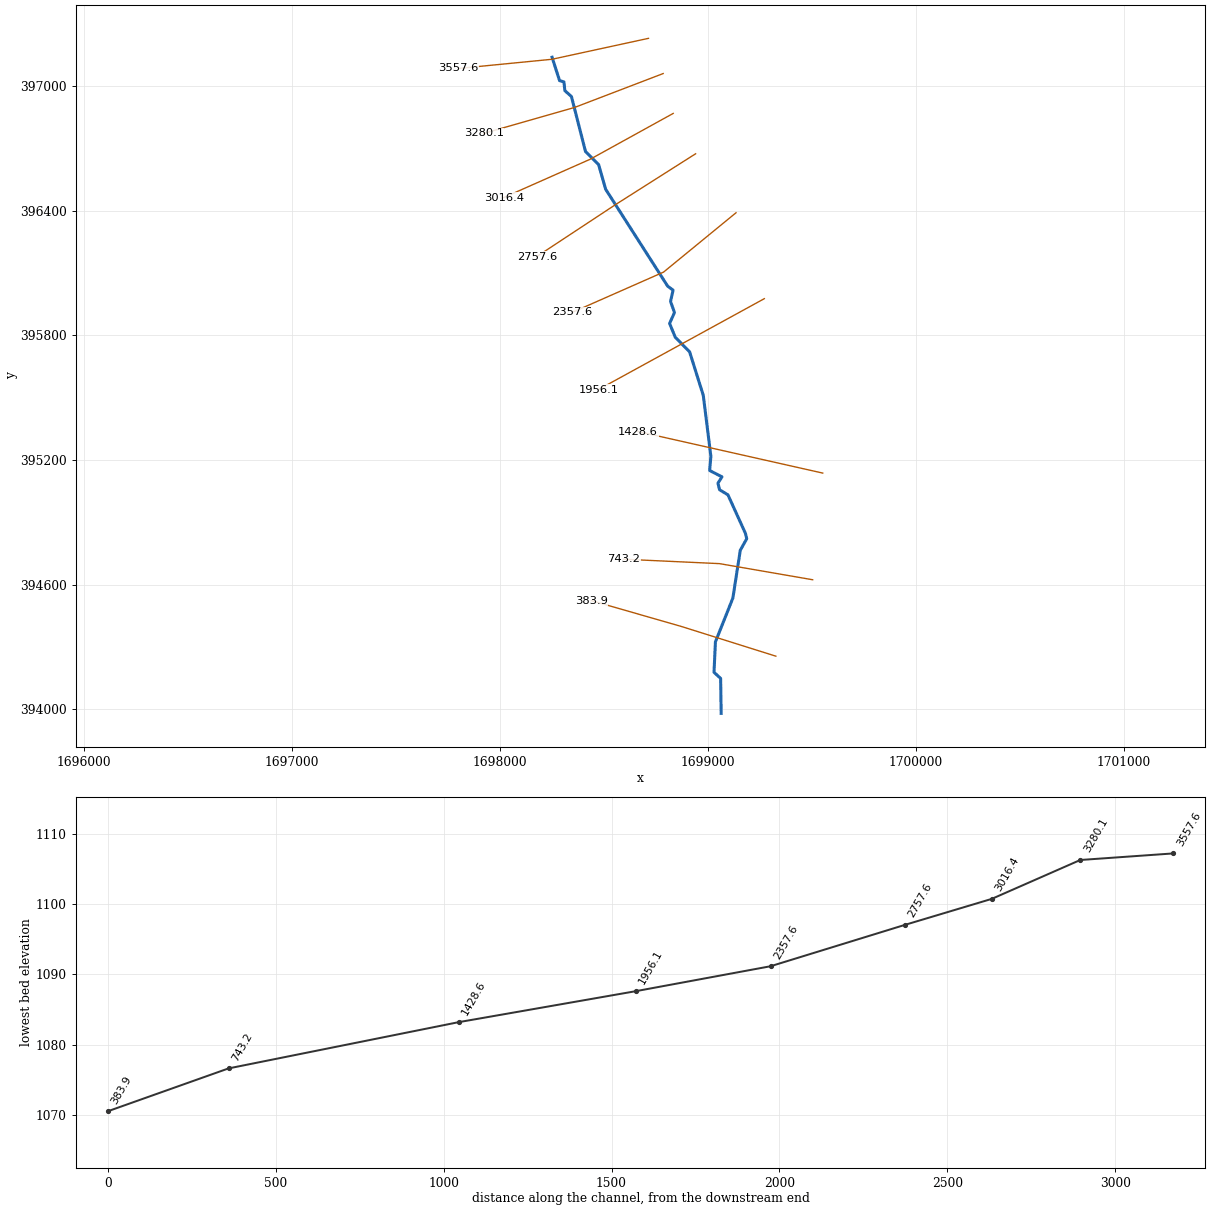
--- NP18.prj (project) ---

Proj Title=NP18
Current Plan=p01
Geom File=g01
Flow File=f01
Plan File=p01
DSS Export Rating Curves=0
DSS Export Rating Curve Sorted=0
DSS Export Volume Flow Curves=0
DXF OffsetX=0
DXF OffsetY=0
DXF ScaleX=0
DXF ScaleY=0

--- NP18.p01 (plan) ---

Plan Title=Floodplain
Program Version=4.00
Geom File=g01
Flow File=f01
K Sum by GR=0
Std Step Tol=0.01
Critical Tol=0.01
Num of Std Step Trials=20
Max Error Tol=0.3
Flow Tol Ratio=0.001
Split Flow NTrial=30
Split Flow Tol=0.02
Split Flow Ratio=0.02
Log Output Level=0
Friction Slope Method=1
Unsteady Friction Slope Method=2
Unsteady Bridges Friction Slope Method=1
Global Log Level=0
CheckData=False
Run HTab=0
Run UNet=0
Run PostProcess=0
UNET Theta=0
UNET Theta Warmup=0
UNET ZTol=0
UNET ZSATol=0
UNET MxIter=0
UNET MaxInSteps=0
UNET DtIC=0
UNET DtMin=0
UNET MaxCRTS=0
UNET WFStab=0
UNET SFStab=0
UNET WFX=0
UNET SFX=0
UNET DSS MLevel=0
UNET DZMax Abort=0
UNET Convert EG Bridges=0
UNET Use Existing IB Tables=0
UNET Froude Limit=0
UNET Froude Power=0
Write IC File=0
Echo Input=False
Echo Output=False
Write Detailed=0

--- NP18.f01 (steady flow) ---

Flow Title=NFF Regression Equation
Program Version=4.00
Number of Profiles=1
Profile Names=P100yr
River Rch & RM=NP18,Main      ,3557.6
594.0086
River Rch & RM=NP18,Main      ,1428.6
637.0555
River Rch & RM=NP18,Main      ,743.2
784.4978
River Rch & RM=NP18,Main      ,383.9
800.5936
Boundary for River Rch & Prof#=NP18,Main      ,1
Up Type=0
Dn Type=3
Dn Slope=0.010634

--- NP18.g01 (geometry) ---

Geom Title=USGS 3m DEM
Program Version=4.00

River Reach=NP18     ,Main
Reach XY= 30
     1698251.540      397139.725     1698287.662      397026.860
     1698308.718      397020.895     1698312.898      396978.717
     1698344.724      396950.288     1698412.301      396685.649
     1698475.273      396622.632     1698509.158      396503.684
     1698807.009      396037.219     1698833.166      396017.645
     1698821.060      395963.427     1698839.956      395909.795
     1698816.435      395857.470     1698843.839      395790.863
     1698912.645      395720.700     1698978.407      395511.101
     1699014.836      395217.974     1699009.095      395149.094
     1699068.072      395118.668     1699049.033      395087.911
     1699056.636      395056.443     1699096.918      395031.956
     1699180.991      394846.527     1699187.233      394820.326
     1699156.262      394765.087     1699120.738      394535.010
     1699036.741      394323.586     1699029.985      394177.227
     1699061.756      394147.701     1699064.359      393979.382

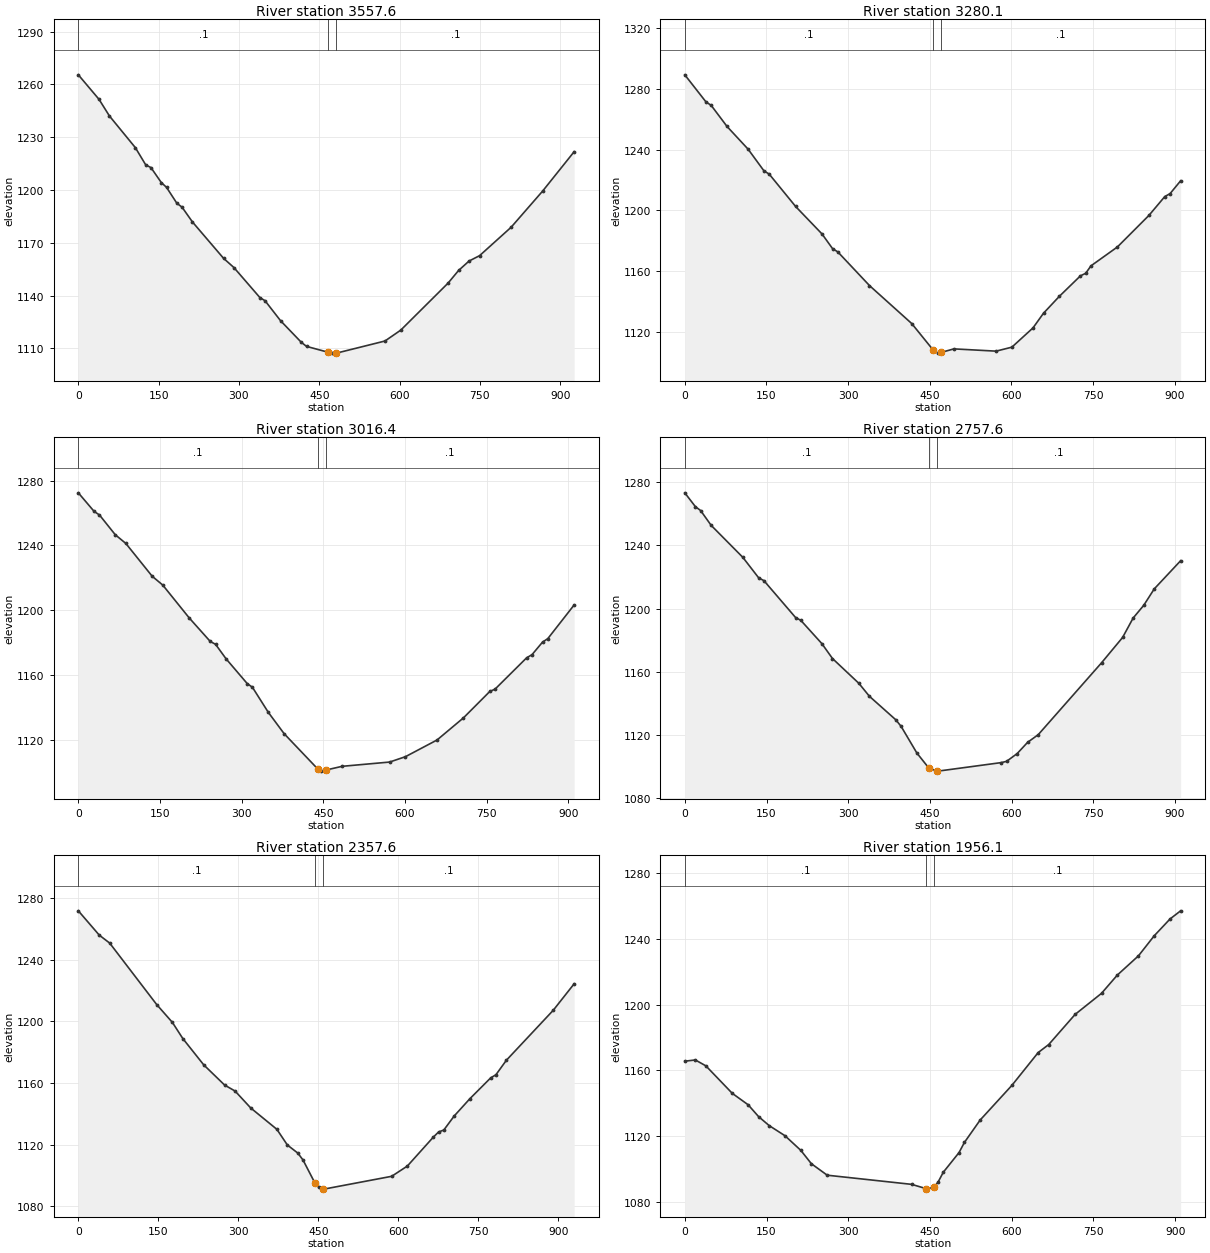
Type RM Length L Ch R = 1 ,3557.6,270.299,277.507,278.913
XS GIS Cut Line= 3
     1698715.196      397230.606     1698251.424      397129.763
     1697802.230      397085.521
#Sta/Elev= 30
       0 1265.42    38.7 1251.47    58.1 1242.03   106.5 1224.04   125.9 1214.23
   135.6 1212.72   155.0 1204.19   164.7 1201.49   184.0 1192.44   193.7 1190.21
   213.1 1181.82   271.2 1161.15   290.6 1155.89   339.0 1138.87   348.7 1137.05
   377.7 1125.68   416.5 1113.40   426.2 1111.10   467.1 1107.72   474.6 1107.27
   482.1 1107.27   572.7 1114.16   602.2 1120.35   690.5 1147.05   710.1 1154.23
   729.7 1159.60   749.4 1162.66   808.2 1178.78   867.1 1199.35   926.0 1221.75
#Mann= 3 , 0 , 0
       0     0.1       0   467.1   0.045       0   482.1     0.1       0
Bank Sta=   467.1,   482.1
Exp/Cntr=0.3,0.1

Type RM Length L Ch R = 1 ,3280.1,259.755,263.696,267.711
XS GIS Cut Line= 3
     1698785.745      397061.067     1698360.329      396897.888
     1697922.675      396772.537
#Sta/Elev= 30
       0 1289.08    38.8 1271.34    48.5 1269.01    77.6 1255.17   116.3 1240.26
   145.4 1226.03   155.1 1223.87   203.6 1202.63   252.1 1184.58   271.4 1174.97
   281.1 1172.80   339.3 1150.69   416.9 1125.76   455.7 1108.63   465.3 1106.33
   470.7 1106.76   494.4 1109.12   571.9 1107.63   600.9 1110.25   639.7 1122.90
   659.0 1132.54   688.1 1143.63   726.9 1157.10   736.5 1158.76   746.2 1163.64
   794.7 1176.03   852.8 1196.82   881.8 1209.14   891.5 1211.06   910.9 1219.50
#Mann= 3 , 0 , 0
       0     0.1       0   455.7   0.045       0   470.7     0.1       0
Bank Sta=   455.7,   470.7
Exp/Cntr=0.3,0.1

Type RM Length L Ch R = 1 ,3016.4,257.83,258.798,261.424
XS GIS Cut Line= 3
     1698833.929      396869.015     1698435.224      396648.469
     1698019.159      396463.690
#Sta/Elev= 30
       0 1272.47    29.1 1260.97    38.8 1258.82    67.9 1246.60    87.2 1241.27
   135.7 1221.00   155.1 1215.56   203.6 1195.34   242.4 1180.76   252.1 1179.02
   271.4 1170.08   310.2 1154.82   319.9 1152.49   349.0 1137.05   378.1 1123.87
   439.9 1102.09   445.9 1100.78   454.9 1101.45   484.7 1103.75   571.9 1106.38
   600.9 1109.68   659.0 1119.99   707.5 1133.63   755.9 1149.92   765.6 1151.37
   823.7 1170.73   833.4 1172.60   852.8 1180.37   862.5 1182.52   910.9 1203.31
#Mann= 3 , 0 , 0
       0     0.1       0   439.9   0.045       0   454.9     0.1       0
Bank Sta=   439.9,   454.9
Exp/Cntr=0.3,0.1

Type RM Length L Ch R = 1 ,2757.6,397.279,400,395.965
XS GIS Cut Line= 3
     1698941.569      396674.630     1698557.604      396430.354
     1698177.985      396179.553
#Sta/Elev= 30
       0 1273.27    19.4 1264.53    29.0 1262.07    48.4 1252.67   106.5 1232.43
   135.6 1219.44   145.2 1217.68   203.3 1194.33   213.0 1192.52   251.7 1177.75
   271.1 1168.35   319.5 1152.66   338.9 1144.44   387.3 1129.57   397.0 1125.43
   426.0 1108.52   447.6 1099.17   462.6 1097.10   464.8 1097.07   580.9 1102.47
   590.6 1103.26   610.0 1108.16   629.3 1115.32   648.7 1120.13   764.9 1165.63
   803.6 1181.70   822.9 1193.98   842.3 1202.00   861.7 1212.45   910.1 1230.28
#Mann= 3 , 0 , 0
       0     0.1       0   447.6   0.045       0   462.6     0.1       0
Bank Sta=   447.6,   462.6
Exp/Cntr=0.3,0.1

Type RM Length L Ch R = 1 ,2357.6,406.882,401.535,402.03
XS GIS Cut Line= 3
     1699135.704      396390.498     1698787.336      396104.600
     1698349.210      395910.939
#Sta/Elev= 30
       0 1271.63    39.2 1255.89    58.8 1250.71   147.0 1210.82   176.3 1199.31
   195.9 1188.82   235.1 1171.76   274.3 1158.65   293.9 1154.77   323.3 1143.78
   372.3 1129.95   391.9 1119.80   411.5 1114.55   421.3 1110.06   443.2 1095.42
   450.7 1092.42   458.2 1091.45   460.4 1091.17   587.5 1099.48   616.9 1106.12
   665.7 1124.91   675.5 1128.23   685.3 1129.50   704.8 1138.61   734.2 1149.81
   773.3 1163.34   783.0 1165.33   802.6 1174.73   890.6 1207.19   929.7 1224.33
#Mann= 3 , 0 , 0
       0     0.1       0   443.2   0.045       0   458.2     0.1       0
Bank Sta=   443.2,   458.2
Exp/Cntr=0.3,0.1

Type RM Length L Ch R = 1 ,1956.1,544.052,527.463,510.874
XS GIS Cut Line= 3
     1699271.873      395976.810     1698873.054      395757.792
     1698474.236      395538.775
#Sta/Elev= 30
       0 1165.54    19.4 1166.28    38.7 1162.69    87.1 1145.96   116.2 1139.00
   135.5 1131.76   154.9 1126.30   183.9 1120.13   213.0 1111.20   232.3 1103.09
   261.4 1096.09   416.3 1090.52     443 1087.90   445.3 1087.61     458 1089.16
   464.7 1091.79   474.4 1097.89   503.4 1109.91   513.1 1116.02   542.1 1129.70
   600.2 1150.76   648.6 1170.80   668.0 1175.70   716.4 1194.04   764.8 1206.86
   793.8 1217.98   832.6 1229.70   861.6 1241.94   890.6 1252.17   910.0 1257.12
#Mann= 3 , 0 , 0
       0     0.1       0     443   0.045       0     458     0.1       0
Bank Sta=     443,     458
Exp/Cntr=0.3,0.1

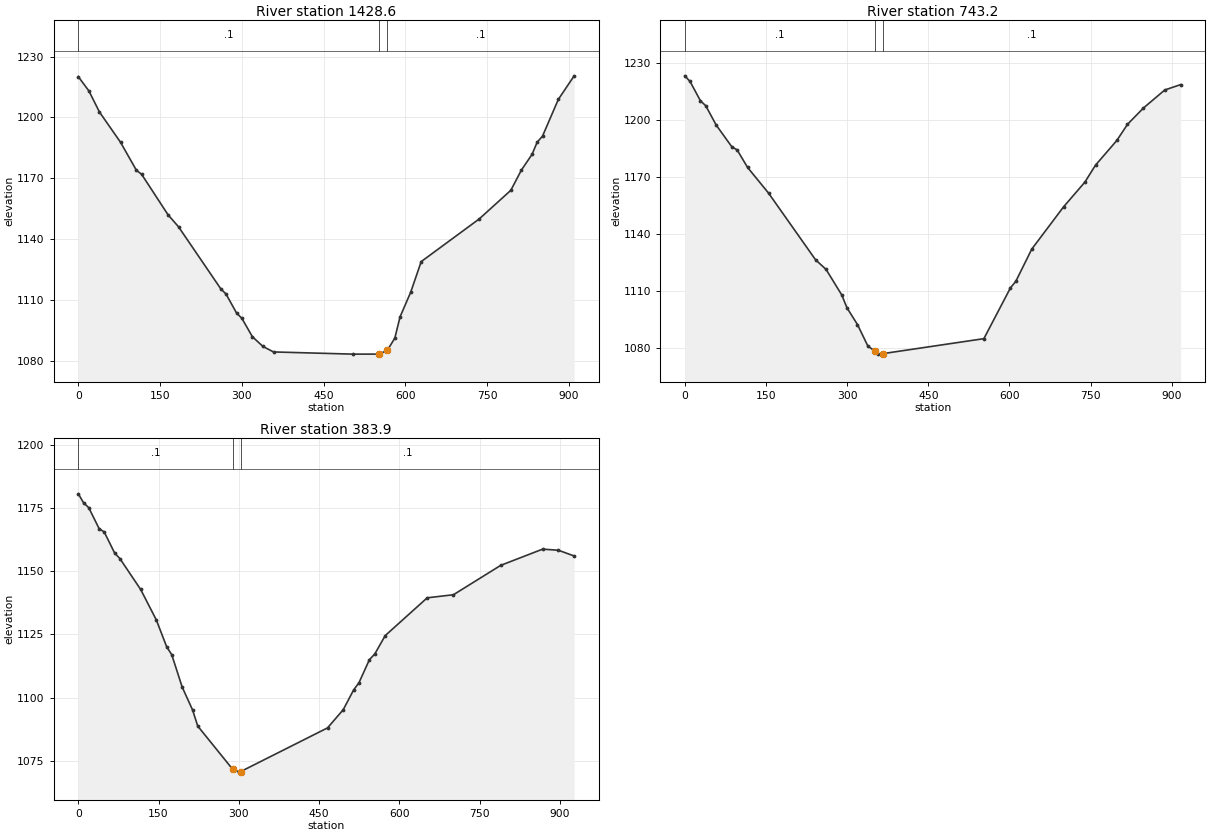
Type RM Length L Ch R = 1 ,1428.6,682.207,685.402,655.036
XS GIS Cut Line= 3
     1699552.676      395136.659     1699108.828      395236.781
     1698664.981      395336.902
#Sta/Elev= 30
       0 1220.14    19.4 1213.12    38.7 1202.74    77.4 1187.79   106.5 1173.97
   116.2 1171.94   164.6 1151.99   183.9 1146.04   261.4 1115.45   271.1 1112.84
   290.4 1103.47   300.1 1100.87   319.5 1091.77   338.8 1086.99   358.2 1084.27
   503.4 1083.19     552 1083.20     567 1085.02   580.9 1091.11   590.5 1101.62
   609.9 1113.68   629.3 1128.87   735.7 1149.91   793.8 1164.07   813.2 1174.06
   832.6 1181.76   842.2 1187.85   851.9 1190.79   881.0 1208.95   910.0 1220.57
#Mann= 3 , 0 , 0
       0     0.1       0     552   0.045       0     567     0.1       0
Bank Sta=     552,     567
Exp/Cntr=0.3,0.1

Type RM Length L Ch R = 1 ,743.2,362.328,359.289,356.25
XS GIS Cut Line= 3
     1699504.122      394623.001     1699056.357      394700.583
     1698594.948      394721.958
#Sta/Elev= 30
       0 1223.26     9.7 1220.28    29.0 1210.06    38.7 1207.51    58.0 1197.32
    87.0 1185.82    96.7 1184.23   116.0 1174.99   154.7 1161.48   241.7 1126.29
   261.1 1121.24   290.1 1107.76   299.7 1100.99   319.1 1092.18   338.4 1080.81
   350.8 1078.27   357.7 1076.59   365.8 1076.84   552.7 1084.74   601.9 1111.56
   611.7 1114.94   641.2 1131.94   700.1 1154.26   739.4 1167.25   759.1 1176.21
   798.4 1189.19   818.1 1197.69   847.5 1206.27   886.9 1215.78   916.3 1218.64
#Mann= 3 , 0 , 0
       0     0.1       0   350.8   0.045       0   365.8     0.1       0
Bank Sta=   350.8,   365.8
Exp/Cntr=0.3,0.1

Type RM Length L Ch R = 1 ,383.9,377.242,383.931,389.831
XS GIS Cut Line= 3
     1699327.287      394254.859     1698873.703      394397.790
     1698440.004      394522.669
#Sta/Elev= 30
       0 1180.59     9.7 1177.06    19.4 1175.14    38.8 1166.84    48.5 1165.47
    67.9 1157.15    77.6 1155.00   116.5 1142.76   145.6 1130.78   165.0 1120.16
   174.7 1116.90   194.1 1104.15   213.5 1095.11   223.2 1088.71   288.3 1071.66
   300.9 1070.48   303.3 1070.68   465.9 1087.99   495.2 1095.18   514.8 1103.06
   524.6 1105.84   544.2 1114.99   554.1 1117.20   573.7 1124.50   652.2 1139.45
   701.2 1140.66   789.5 1152.28   868.0 1158.71   897.5 1158.26   926.9 1156.00
#Mann= 3 , 0 , 0
       0     0.1       0   288.3   0.045       0   303.3     0.1       0
Bank Sta=   288.3,   303.3
Exp/Cntr=0.3,0.1